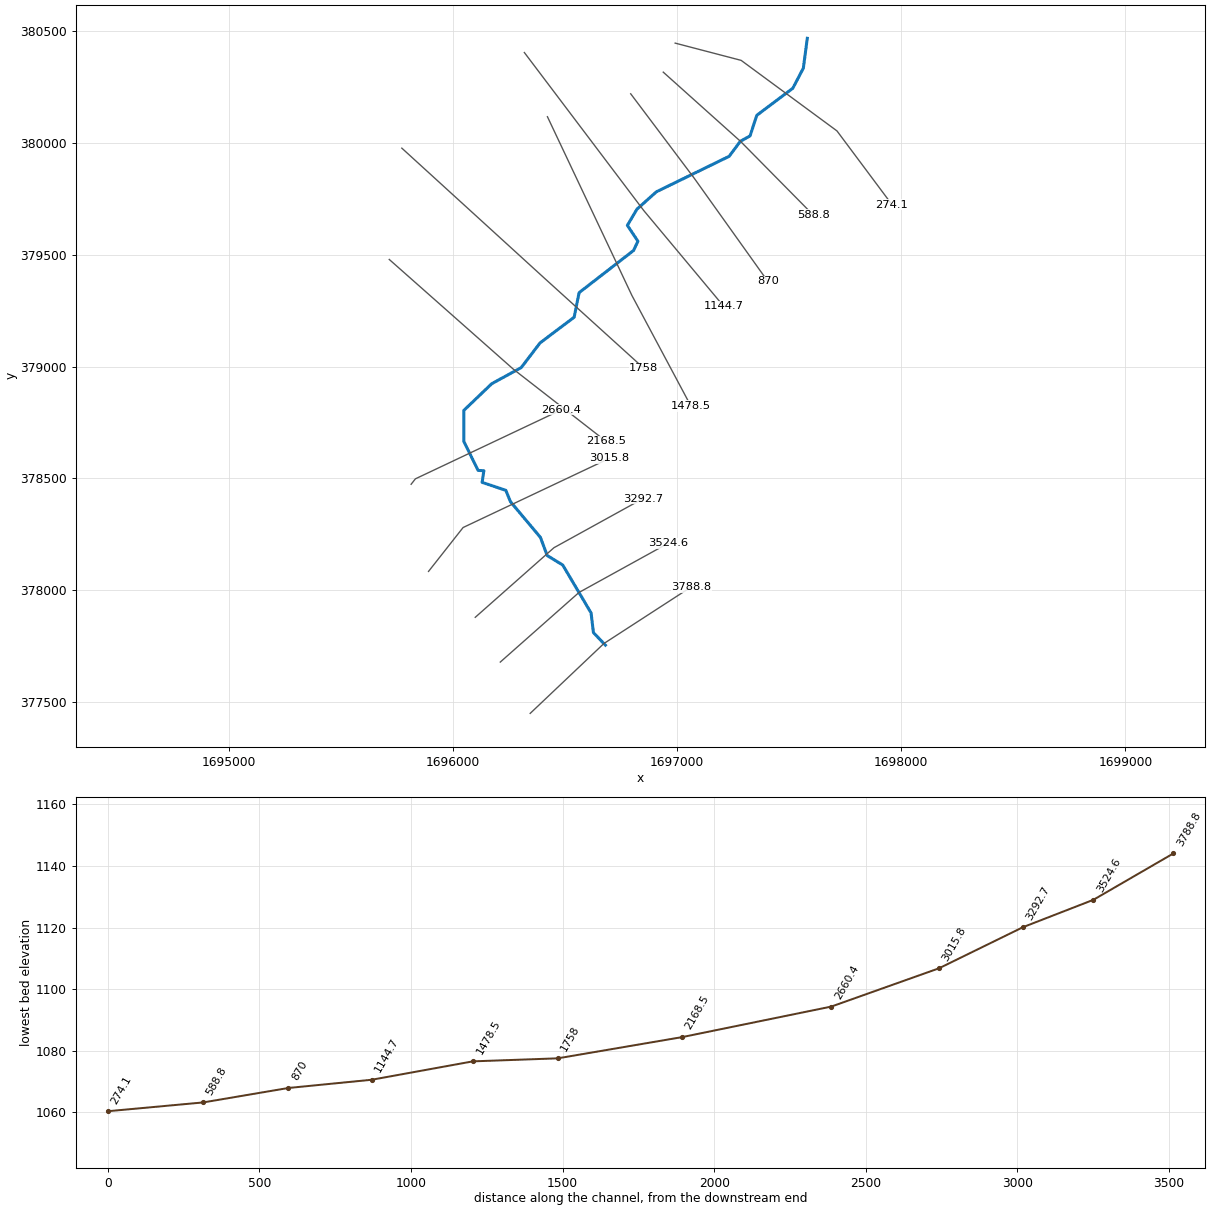
--- Trb1BUFF.prj (project) ---

Proj Title=Trb1BUFF
Current Plan=p01
Geom File=g01
Flow File=f01
Plan File=p01
DSS Export Rating Curves=0
DSS Export Rating Curve Sorted=0
DSS Export Volume Flow Curves=0
DXF OffsetX=0
DXF OffsetY=0
DXF ScaleX=0
DXF ScaleY=0

--- Trb1BUFF.p01 (plan) ---

Plan Title=Floodplain
Program Version=4.00
Geom File=g01
Flow File=f01
K Sum by GR=0
Std Step Tol=0.01
Critical Tol=0.01
Num of Std Step Trials=20
Max Error Tol=0.3
Flow Tol Ratio=0.001
Split Flow NTrial=30
Split Flow Tol=0.02
Split Flow Ratio=0.02
Log Output Level=0
Friction Slope Method=1
Unsteady Friction Slope Method=2
Unsteady Bridges Friction Slope Method=1
Global Log Level=0
CheckData=False
Run HTab=0
Run UNet=0
Run PostProcess=0
UNET Theta=0
UNET Theta Warmup=0
UNET ZTol=0
UNET ZSATol=0
UNET MxIter=0
UNET MaxInSteps=0
UNET DtIC=0
UNET DtMin=0
UNET MaxCRTS=0
UNET WFStab=0
UNET SFStab=0
UNET WFX=0
UNET SFX=0
UNET DSS MLevel=0
UNET DZMax Abort=0
UNET Convert EG Bridges=0
UNET Use Existing IB Tables=0
UNET Froude Limit=0
UNET Froude Power=0
Write IC File=0
Echo Input=False
Echo Output=False
Write Detailed=0

--- Trb1BUFF.f01 (steady flow) ---

Flow Title=NFF Regression Equation
Program Version=4.00
Number of Profiles=1
Profile Names=P100yr
River Rch & RM=Trb1BUFF,Main      ,3788.8
148.7734
River Rch & RM=Trb1BUFF,Main      ,3524.6
148.7734
River Rch & RM=Trb1BUFF,Main      ,3292.7
172.7258
River Rch & RM=Trb1BUFF,Main      ,3015.8
183.8811
River Rch & RM=Trb1BUFF,Main      ,2660.4
194.5918
River Rch & RM=Trb1BUFF,Main      ,2168.5
483.9872
River Rch & RM=Trb1BUFF,Main      ,1758
489.6020
River Rch & RM=Trb1BUFF,Main      ,274.1
538.2984
Boundary for River Rch & Prof#=Trb1BUFF,Main      ,1
Up Type=0
Dn Type=3
Dn Slope=0.013172

--- Trb1BUFF.g01 (geometry) ---

Geom Title=USGS 3m DEM
Program Version=4.00

River Reach=Trb1BUFF     ,Main
Reach XY= 30
     1696679.843      377753.979     1696626.401      377810.242
     1696615.856      377898.287     1696489.447      378112.327
     1696420.019      378154.900     1696389.965      378235.888
     1696256.166      378395.540     1696235.389      378446.446
     1696129.762      378481.960     1696137.462      378534.086
     1696111.849      378535.400     1696047.854      378665.298
     1696047.875      378803.545     1696172.663      378923.231
     1696304.171      378995.216     1696388.003      379105.328
     1696540.352      379220.507     1696562.428      379330.245
     1696805.635      379519.069     1696824.848      379560.325
     1696777.853      379631.113     1696820.712      379703.746
     1696907.738      379781.524     1697231.934      379939.929
     1697281.825      380007.114     1697325.343      380031.135
     1697355.120      380122.961     1697516.081      380244.220
     1697563.093      380334.152     1697580.737      380467.570

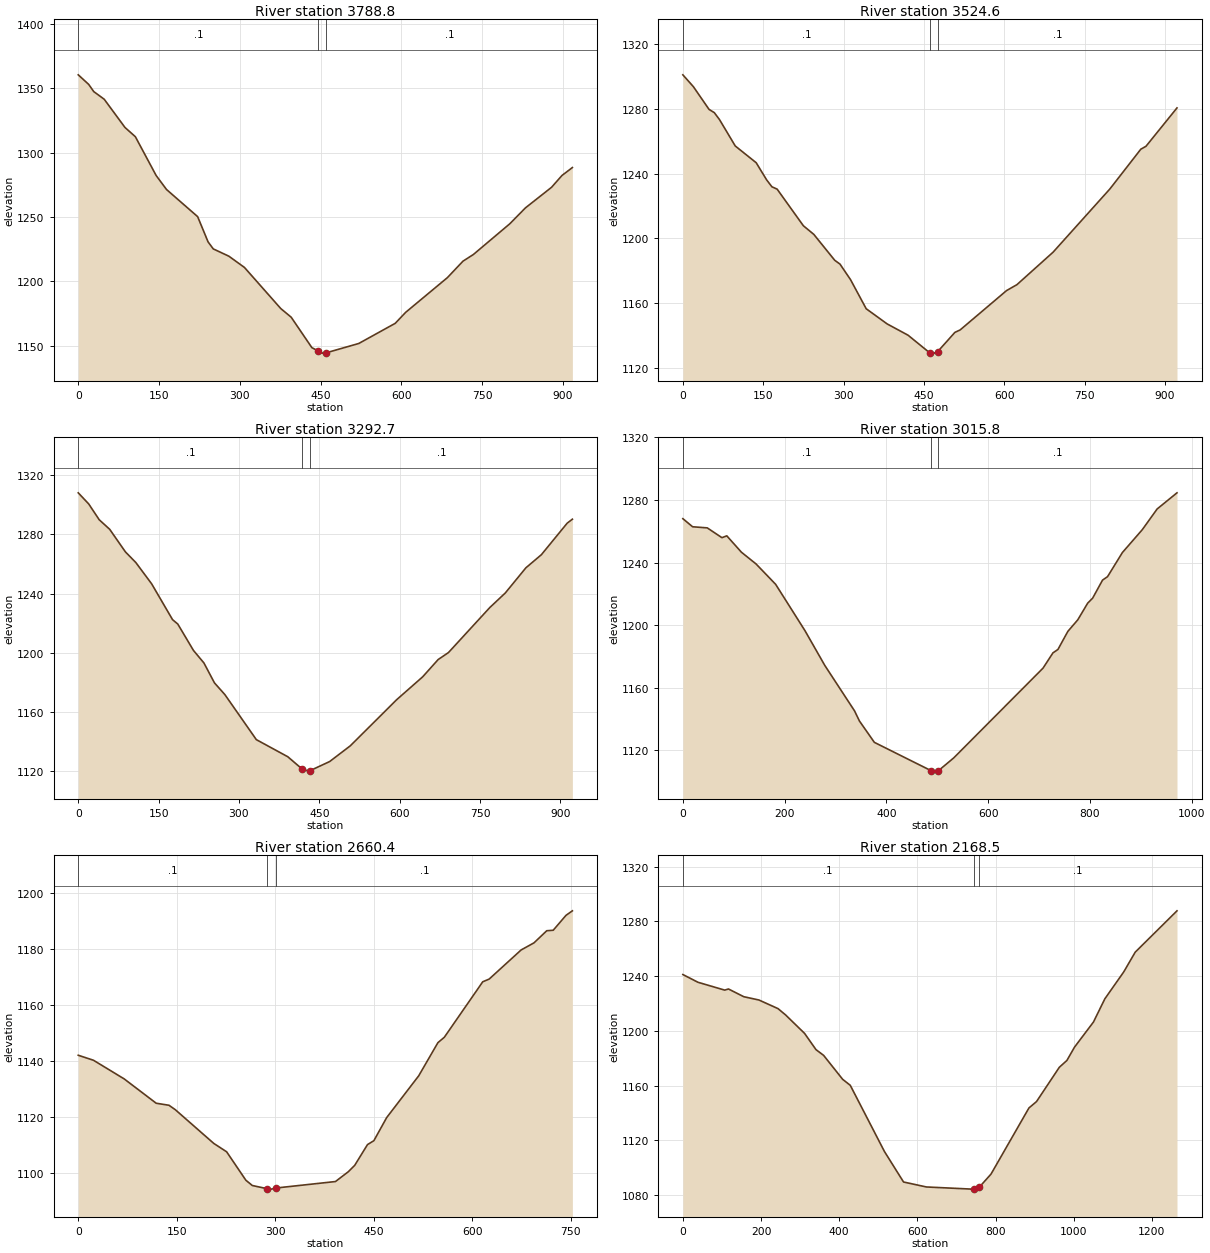
Type RM Length L Ch R = 1 ,3788.8,265.783,264.191,261.995
XS GIS Cut Line= 3
     1696344.267      377449.020     1696672.956      377761.229
     1697062.432      378014.243
#Sta/Elev= 30
       0 1360.49    19.3 1353.09    28.9 1347.42    48.2 1341.52    86.8 1319.57
   106.1 1312.36   144.7 1282.19   164.0 1271.30   221.8 1250.20   241.1 1230.61
   250.8 1225.13   279.7 1219.47   308.7 1210.71   376.2 1178.72   395.5 1172.02
   434.0 1148.31   445.8 1145.79   453.3 1144.08   460.8 1144.36   521.1 1151.59
   588.8 1167.26   608.1 1175.78   685.6 1202.76   714.6 1215.58   733.9 1220.77
   801.7 1244.71   830.7 1257.06   879.1 1273.03   898.4 1282.19   917.8 1288.39
#Mann= 3 , 0 , 0
       0     0.1       0   445.8   0.045       0   460.8     0.1       0
Bank Sta=   445.8,   460.8
Exp/Cntr=0.3,0.1

Type RM Length L Ch R = 1 ,3524.6,231.497,231.893,237.07
XS GIS Cut Line= 3
     1696210.738      377678.408     1696561.937      377989.697
     1696958.366      378208.807
#Sta/Elev= 30
       0 1301.22    19.6 1293.91    48.9 1279.82    58.7 1277.82    68.4 1273.52
    97.8 1257.19   136.9 1246.82   156.4 1236.20   166.2 1231.94   176.0 1230.47
   224.9 1207.83   244.4 1202.49   283.5 1186.44   293.3 1184.08   312.9 1174.51
   342.2 1156.46   381.3 1147.07   420.4 1140.07   460.7 1129.20   469.3 1128.99
   475.7 1129.95   507.8 1141.84   517.5 1143.33   604.2 1167.70   623.5 1171.35
   691.0 1191.45   797.0 1230.57   854.8 1255.20   864.4 1256.99   922.3 1280.74
#Mann= 3 , 0 , 0
       0     0.1       0   460.7   0.045       0   475.7     0.1       0
Bank Sta=   460.7,   475.7
Exp/Cntr=0.3,0.1

Type RM Length L Ch R = 1 ,3292.7,283.973,276.968,269.963
XS GIS Cut Line= 3
     1696099.050      377878.553     1696450.249      378189.841
     1696846.678      378408.951
#Sta/Elev= 30
       0 1308.09    19.6 1300.56    39.1 1289.92    58.7 1283.45    88.0 1268.22
   107.5 1260.99   136.9 1246.68   176.0 1222.44   185.8 1219.44   215.1 1201.62
   234.6 1193.16   254.2 1179.74   273.8 1171.75   332.4 1141.38   391.1 1129.83
   418.3 1121.40   430.2 1120.11   433.3 1120.53   469.3 1126.59   507.8 1137.21
   594.6 1168.45   642.8 1183.78   671.7 1195.45   691.0 1200.19   768.1 1230.58
   797.0 1240.41   835.5 1257.43   864.4 1266.28   912.6 1287.59   922.3 1290.28
#Mann= 3 , 0 , 0
       0     0.1       0   418.3   0.045       0   433.3     0.1       0
Bank Sta=   418.3,   433.3
Exp/Cntr=0.3,0.1

Type RM Length L Ch R = 1 ,3015.8,338.445,355.347,339.229
XS GIS Cut Line= 3
     1695890.561      378083.808     1696044.781      378280.088
     1696696.882      378589.042
#Sta/Elev= 30
       0 1267.99    19.2 1262.82    48.0 1262.11    76.8 1255.86    86.4 1257.02
   115.2 1246.54   144.0 1239.03   182.4 1226.05   240.0 1196.47   278.9 1174.31
   337.4 1145.25   347.1 1138.75   376.4 1125.12   487.3 1107.14   493.4 1106.75
   502.3 1107.02   532.4 1115.20   707.9 1172.52   727.4 1182.28   737.2 1184.45
   756.7 1196.00   776.2 1203.38   795.7 1214.04   805.4 1217.22   824.9 1228.76
   834.7 1230.95   863.9 1246.36   902.9 1260.92   932.2 1274.19   971.2 1284.50
#Mann= 3 , 0 , 0
       0     0.1       0   487.3   0.045       0   502.3     0.1       0
Bank Sta=   487.3,   502.3
Exp/Cntr=0.3,0.1

Type RM Length L Ch R = 1 ,2660.4,516.825,491.896,467.742
XS GIS Cut Line= 3
     1695812.883      378473.512     1695831.992      378497.831
     1696484.093      378806.785
#Sta/Elev= 30
       0 1142.13    23.2 1140.34    69.9 1133.69   118.7 1124.99   138.2 1124.26
   147.9 1122.66   206.4 1110.63   226.0 1107.63   255.2 1097.50   265.0 1095.60
   286.9 1094.49   294.2 1094.30   301.9 1094.72   391.7 1097.01   411.2 1100.50
   421.0 1102.79   440.5 1110.21   450.2 1111.61   469.7 1119.86   518.5 1134.79
   547.7 1146.62   557.5 1148.56   616.0 1168.38   625.8 1169.35   674.5 1179.76
   694.0 1182.28   713.5 1186.62   723.3 1186.79   742.8 1192.12   752.5 1193.73
#Mann= 3 , 0 , 0
       0     0.1       0   286.9   0.045       0   301.9     0.1       0
Bank Sta=   286.9,   301.9
Exp/Cntr=0.3,0.1

Type RM Length L Ch R = 1 ,2168.5,417.597,410.494,401.722
XS GIS Cut Line= 3
     1695715.311      379478.800     1696269.101      378988.099
     1696682.692      378665.639
#Sta/Elev= 30
       0 1241.19    38.9 1235.51   107.1 1229.80   116.8 1230.63   155.8 1224.99
   194.7 1222.57   243.4 1216.30   262.9 1211.66   311.5 1198.17   340.7 1186.30
   360.2 1182.11   408.9 1164.63   428.4 1160.23   516.0 1111.79   564.7 1089.59
   623.1 1085.96   739.9 1084.38   743.8 1084.47   758.8 1085.88   788.5 1095.36
   885.6 1143.70   905.0 1148.37   963.3 1173.40   982.7 1178.40  1002.1 1188.09
  1050.7 1206.50  1079.8 1223.44  1128.4 1243.22  1157.5 1257.54  1264.4 1287.74
#Mann= 3 , 0 , 0
       0     0.1       0   743.8   0.045       0   758.8     0.1       0
Bank Sta=   743.8,   758.8
Exp/Cntr=0.3,0.1

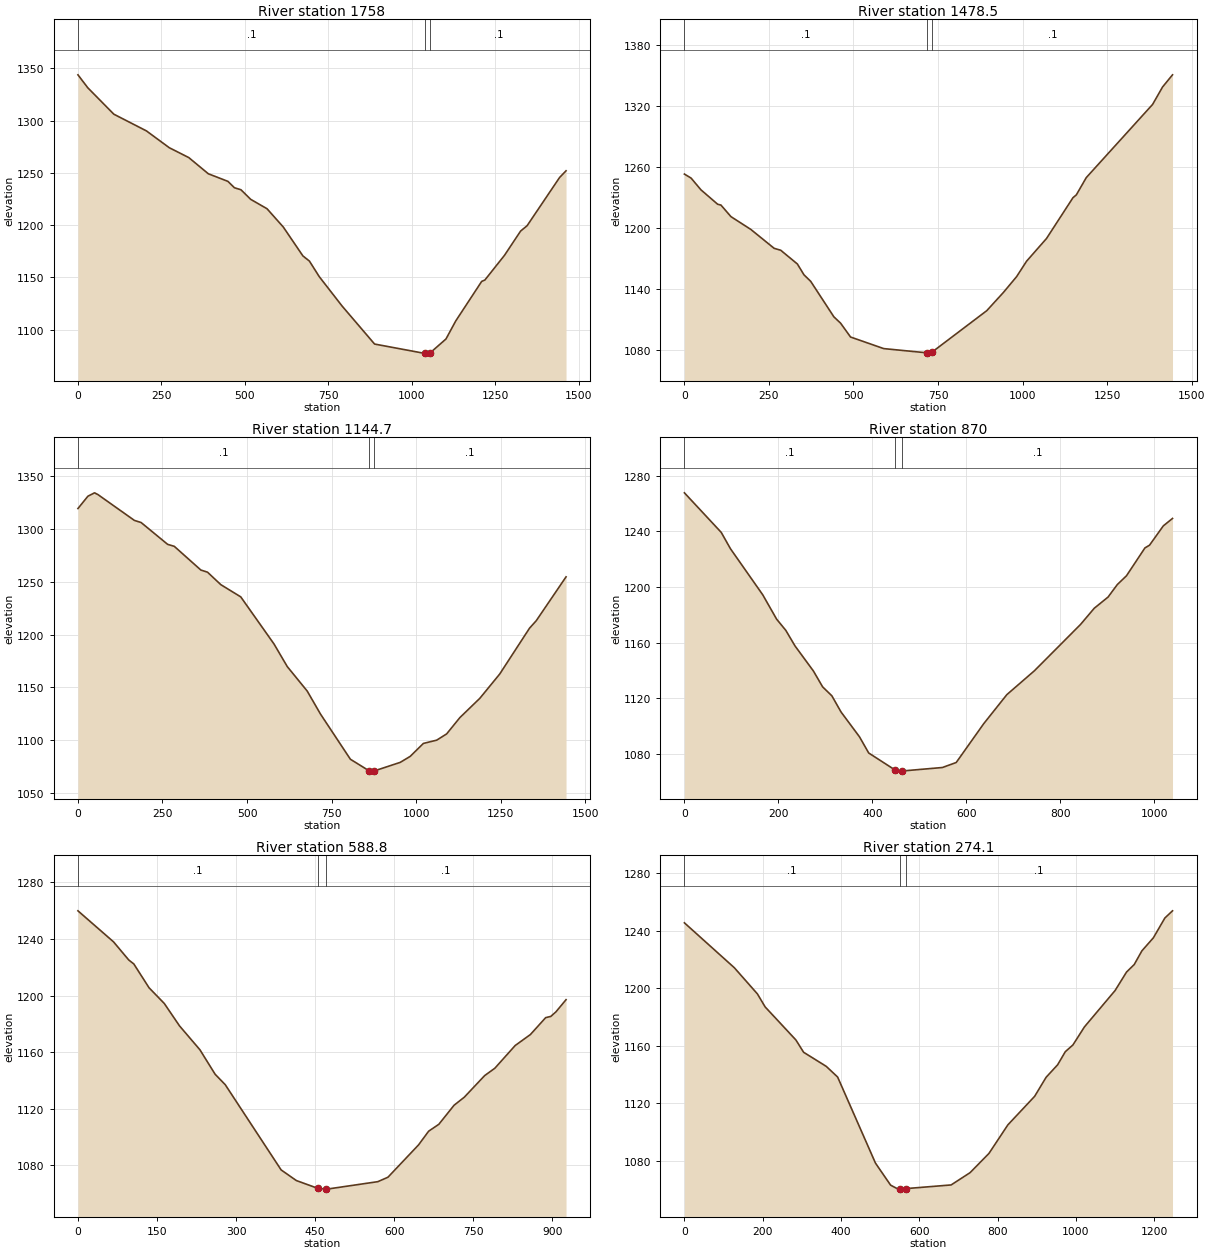
Type RM Length L Ch R = 1 ,1758,282.872,279.535,277.092
XS GIS Cut Line= 3
     1695771.391      379976.511     1696405.482      379397.072
     1696851.384      378992.156
#Sta/Elev= 30
       0 1343.94    29.3 1331.61   107.4 1306.26   205.0 1290.26   273.3 1274.18
   331.9 1264.69   390.4 1249.20   449.0 1241.93   468.5 1235.82   488.0 1233.91
   517.3 1224.70   566.1 1215.73   614.9 1198.15   673.5 1170.56   693.0 1165.61
   722.3 1150.77   790.6 1122.65   888.1 1086.16  1033.8 1077.48  1040.4 1077.61
  1055.4 1078.01  1101.8 1091.01  1131.0 1108.25  1208.7 1146.13  1218.4 1147.52
  1276.7 1170.99  1325.3 1194.34  1344.7 1199.47  1441.9 1245.61  1461.3 1252.05
#Mann= 3 , 0 , 0
       0     0.1       0  1040.4   0.045       0  1055.4     0.1       0
Bank Sta=  1040.4,  1055.4
Exp/Cntr=0.3,0.1

Type RM Length L Ch R = 1 ,1478.5,328.236,333.782,339.389
XS GIS Cut Line= 3
     1696421.122      380117.105     1696798.331      379317.302
     1697061.129      378823.811
#Sta/Elev= 30
       0 1252.73    19.7 1248.79    49.1 1237.17    98.3 1223.04   108.1 1222.21
   137.6 1210.85   196.5 1198.24   265.3 1179.66   284.9 1177.74   334.1 1164.23
   353.7 1153.51   373.4 1147.20   442.1 1112.18   461.8 1106.02   491.3 1092.35
   589.5 1080.95     718 1076.76   727.1 1076.50     733 1077.69   894.1 1118.28
   943.1 1136.14   982.4 1151.80  1011.8 1166.97  1070.7 1189.28  1149.1 1229.50
  1158.9 1232.23  1188.4 1249.27  1384.5 1321.29  1414.0 1338.46  1443.4 1350.42
#Mann= 3 , 0 , 0
       0     0.1       0     718   0.045       0     733     0.1       0
Bank Sta=     718,     733
Exp/Cntr=0.3,0.1

Type RM Length L Ch R = 1 ,1144.7,274.661,274.7,274.223
XS GIS Cut Line= 3
     1696318.172      380404.121     1696850.540      379698.037
     1697208.443      379268.500
#Sta/Elev= 30
       0 1319.43    29.5 1331.11    49.1 1334.31    59.0 1332.67   167.0 1308.16
   186.7 1306.18   265.3 1285.46   284.9 1283.59   363.5 1261.13   383.2 1259.08
   422.5 1247.27   481.4 1235.70   579.7 1191.08   619.0 1169.63   678.0 1146.40
   717.3 1124.58   805.7 1081.78   859.5 1071.11   874.5 1070.52   953.0 1078.81
   982.4 1084.47  1021.6 1096.79  1060.9 1099.87  1090.3 1105.80  1129.5 1121.28
  1188.4 1139.52  1247.2 1162.53  1335.5 1206.05  1355.1 1213.02  1443.4 1254.66
#Mann= 3 , 0 , 0
       0     0.1       0   859.5   0.045       0   874.5     0.1       0
Bank Sta=   859.5,   874.5
Exp/Cntr=0.3,0.1

Type RM Length L Ch R = 1 ,870,273.545,281.194,285.507
XS GIS Cut Line= 3
     1696792.714      380219.588     1697075.253      379843.320
     1697404.723      379380.660
#Sta/Elev= 30
       0 1267.64    78.4 1239.22    98.0 1227.49   166.6 1194.47   196.1 1177.00
   215.7 1168.92   235.3 1157.74   274.5 1139.71   294.1 1128.33   313.7 1121.92
   333.3 1110.29   372.5 1092.49   392.1 1080.87   448.6 1068.58   460.7 1067.85
   463.6 1067.95   548.9 1070.45   578.3 1074.04   637.0 1101.99   686.0 1122.75
   744.7 1139.91   842.7 1173.11   872.0 1184.78   901.4 1192.81   921.0 1201.76
   940.6 1208.10   979.8 1228.08   989.6 1230.05  1018.9 1243.91  1038.5 1249.24
#Mann= 3 , 0 , 0
       0     0.1       0   448.6   0.045       0   463.6     0.1       0
Bank Sta=   448.6,   463.6
Exp/Cntr=0.3,0.1

Type RM Length L Ch R = 1 ,588.8,311.758,314.754,319.492
XS GIS Cut Line= 3
     1696938.003      380316.379     1697282.196      380007.424
     1697607.397      379677.459
#Sta/Elev= 30
       0 1259.90    67.5 1237.97    96.4 1225.14   106.0 1222.33   134.9 1205.49
   163.8 1194.39   192.7 1178.54   231.3 1161.70   260.2 1144.37   279.4 1136.98
   385.4 1076.73   414.3 1069.21     455 1063.70     470 1063.18   472.2 1063.15
   568.7 1068.42   588.0 1071.56   645.9 1094.36   665.2 1104.11   684.5 1108.98
   713.5 1122.48   732.8 1128.14   771.4 1143.40   790.7 1148.60   829.3 1164.67
   858.2 1172.44   887.2 1184.40   896.8 1185.24   906.5 1188.44   925.8 1197.08
#Mann= 3 , 0 , 0
       0     0.1       0     455   0.045       0     470     0.1       0
Bank Sta=     455,     470
Exp/Cntr=0.3,0.1

Type RM Length L Ch R = 1 ,274.1,263.437,274.079,284.721
XS GIS Cut Line= 4
     1696991.133      380446.181     1697285.553      380369.071
     1697713.163      380053.621     1697958.514      379724.150
#Sta/Elev= 30
       0 1245.56   127.6 1214.29   186.5 1196.09   206.2 1187.05   284.7 1164.07
   304.4 1155.51   362.3 1145.69   391.3 1138.26   487.9 1078.40   526.6 1063.05
   545.9 1060.29   550.3 1060.35   565.3 1060.64   681.1 1063.20   729.5 1071.74
   777.8 1085.15   826.1 1105.02   894.4 1124.85   923.8 1138.14   953.1 1146.79
   972.7 1155.90   992.2 1160.61  1021.6 1173.16  1099.8 1198.44  1129.1 1211.32
  1148.7 1216.54  1168.3 1226.07  1197.6 1235.12  1227.0 1248.93  1246.5 1253.91
#Mann= 3 , 0 , 0
       0     0.1       0   550.3   0.045       0   565.3     0.1       0
Bank Sta=   550.3,   565.3
Exp/Cntr=0.3,0.1